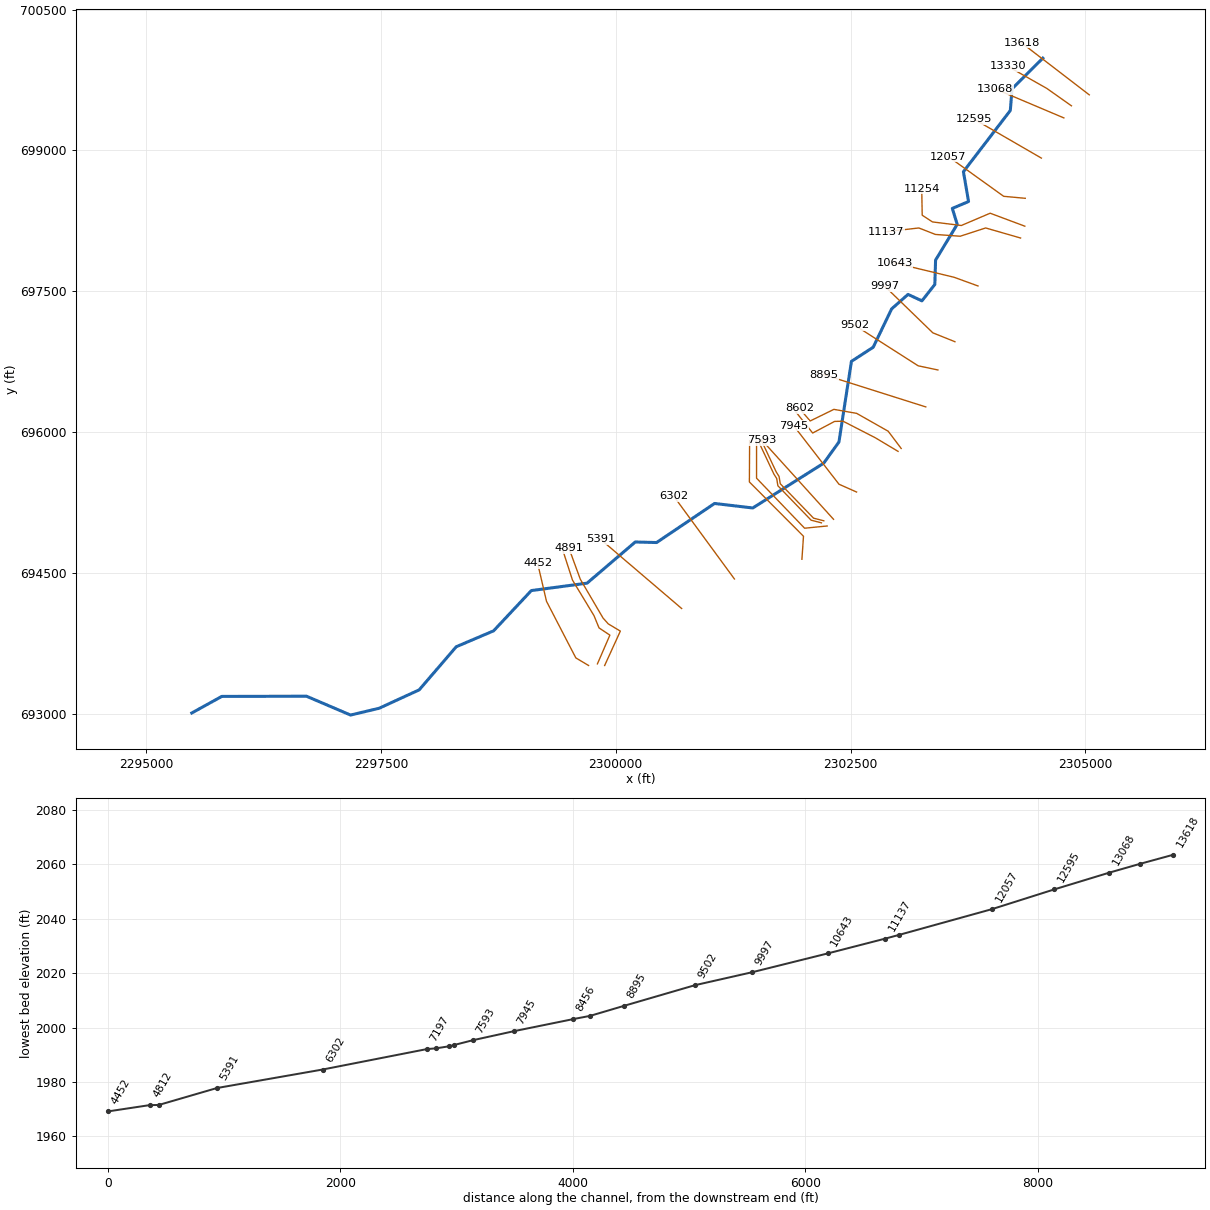
--- ISNERCK_L.prj (project) ---

Proj Title=ISNERCK_L
Current Plan=p01
Default Exp/Contr=0,0
English Units
Geom File=g01
Flow File=f01
Plan File=p01
BEGIN DESCRIPTION:
----------MODEL BY WSP USA 2022----------
AFH study
Randolph County, WV
HEC-RAS Version: RAS 6.2
Vertical Datum: NAVD88
Projection: NAD 1983 StatePlane West Virginia S FIPS 4702 (US Feet)
Terrain: 1-meter LIDAR (FEMA Region III 3DEP collected 2016-2018)
Land Use: 2019 NLCD
Hydrologic Method:
WV SIR2010-5033 regression equations
Additional Model Notes:
Formerly ISNERCK
Model was split at confluence with POERN; this model is the lower reach
END DESCRIPTION:
DSS Export Rating Curves= 0
DSS Export Rating Curve Sorted= 0
DSS Export Volume Flow Curves= 0
DXF OffsetX= 0
DXF OffsetY= 0
DXF ScaleX= 0
DXF ScaleY= 0

--- ISNERCK_L.p01 (plan) ---

Plan Title=Floodplain
Program Version=6.20
Short Identifier=Floodplain
Geom File=g01
Flow File=f01
Subcritical Flow
K Sum by GR= 0
Std Step Tol= 0.01
Critical Tol= 0.01
Num of Std Step Trials= 20
Max Error Tol= 0.3
Flow Tol Ratio= 0.001
Split Flow NTrial= 30
Split Flow Tol= 0.02
Split Flow Ratio= 0.02
Log Output Level= 0
Friction Slope Method= 1
Unsteady Friction Slope Method= 2
Unsteady Bridges Friction Slope Method= 1
Parabolic Critical Depth
Global Vel Dist= 0 , 0 , 0
Global Log Level= 0
CheckData=True
Encroach Param=-1 ,0,0, 0
Mapping Interval=1HOUR
Computation Time Step Use Courant=        0
Computation Time Step Use Time Series=    0
Computation Time Step Count To Double=0
Computation Time Step Max Doubling=0
Computation Time Step Max Halving=0
Computation Time Step Residence Courant=0
Run HTab= 0
Run UNet= 0
Run Sediment= 0
Run PostProcess= 0
Run WQNet= 0
Run RASMapper=-1
UNET Theta= 0
UNET Theta Warmup= 0
UNET ZTol= 0
UNET ZSATol= 0
UNET MxIter= 0
UNET Max Iter WO Improvement= 0
UNET MaxInSteps= 0
UNET DtIC= 0
UNET DtMin= 0
UNET MaxCRTS= 0
UNET WFStab= 0
UNET SFStab= 0
UNET WFX= 1
UNET SFX= 1
UNET Gravity=32.174
UNET 1D Methodology=Finite Difference
UNET DSS MLevel= 1
UNET Pardiso=0
UNET DZMax Abort= 0
UNET Use Existing IB Tables= 0
UNET Froude Reduction=False
UNET Froude Limit= 0
UNET Froude Power= 0
UNET D1 Cores= 0
UNET WindReference=Eulerian
UNET WindDragFormulation=Hsu (1988)
UNET D2 Coriolis=0
UNET D2 Cores= 0
UNET D2 Theta= 1
UNET D2 Theta Warmup= 1
UNET D2 Z Tol= 0.01
UNET D2 Volume Tol= 0.01
UNET D2 Max Iterations= 20
UNET D2 Equation= 0
UNET D2 RampUpFraction=0.1
UNET D2 TimeSlices= 1
UNET D2 Turbulence Formulation=Non-Conservative (original)
UNET D2 Eddy Viscosity=0.3
UNET D2 Transverse Eddy Viscosity=0.1
UNET D2 Smagorinsky Mixing=0
UNET D2 BCVolumeCheck=0
UNET D2 Cores=0
UNET D2 SolverType=PARDISO (Direct)
UNET D2 Minimum Iterations= 2147483647
UNET D2 Maximum Iterations= 2147483647
UNET D2 Restart Number= 10
UNET D2 Relaxation Coeff=1.3
UNET D2 SOR Precondition Iterations= 10
UNET D2 ILUT Maximum Fill= 8
UNET D2 ILUT Tolerance=1E-08
UNET D1D2 MaxIter= 0
UNET D1D2 ZTol=0.01
UNET D1D2 QTol=0.1
UNET D1D2 MinQTol=1
Write IC File= 0
Write IC File at Fixed DateTime=0
Write IC File at Sim End=0
Echo Input=False
Echo Parameters=False
Echo Output=False
Write Detailed= 0
HDF Write Warmup=0
HDF Write Time Slices=0
HDF Flush=0
HDF Compression= 1
HDF Chunk Size= 1
HDF Spatial Parts= 1
HDF Use Max Rows=0
HDF Fixed Rows= 1
Calibration Method= 0
Calibration Iterations= 20
Calibration Max Change=0.05
Calibration Tolerance=0.2
Calibration Maximum=1.5
Calibration Minimum=0.5
Calibration Optimization Method= 1
WQ AD Non Conservative
WQ ULTIMATE=-1
WQ Max Comp Step=1HOUR
WQ Output Interval=15MIN
WQ Output Selected Increments= 0
WQ Output face flow=0
WQ Output face velocity=0
WQ Output face area=0
WQ Output face dispersion=0
WQ Output cell volume=0
WQ Output cell surface area=0
WQ Output cell continuity=0
WQ Output cumulative cell continuity=0
WQ Output face conc=0
WQ Output face dconc_dx=0
WQ Output face courant=0
WQ Output face peclet=0
WQ Output face adv mass=0
WQ Output face disp mass=0
WQ Output cell mass=0
WQ Output cell source sink temp=0
WQ Output nsm pathways=0
WQ Output nsm derived pathways=0
WQ Create Restart=0
WQ Fixed Restart=0
WQ System Summary=0
WQ Write To DSS=0
Sorting and Armoring Iterations= 10
XS Update Threshold= 0.02
Bed Roughness Predictor= 0
Hydraulics Update Threshold= 0.02
Energy Slope Method= 1
Volume Change Method= 1
Sediment Retention Method= 0
Sediment TS Multiplier= 1
Warm Up Method= 0
XS Weighting Method= 0
Number of US Weighted Cross Sections= 1
Number of DS Weighted Cross Sections= 1
Upstream XS Weight=0
Main XS Weight=1
Downstream XS Weight=0
Number of DS XS's Weighted with US Boundary= 1
Upstream Boundary Weight= 1
Weight of XSs Associated with US Boundary= 0
Number of US XS's Weighted with DS Boundary= 1
Downstream Boundary Weight= 0.5
Weight of XSs Associated with DS Boundary= 0.5
Percentile Method= 0
Sediment Output Level= 3
Mass or Volume Output= 0
Output Increment Type= 1
Profile and TS Output Increment= 1
Transport Output Increment 1
XS Output Flag= 0
XS Output Increment= 10
Read HDF5 Sediment Hotstart= 0
Sediment Hotstart Type= 0
Write Gradation File= 0
Read Gradation Hotstart= 0
Write HDF5 File= 1
Write Binary Output= 1
Write DSS Sediment File= 0
DSS Sediment Output Type= 1
SV Curve= 0
Specific Gage Flag= 0
Subcell Erosion Methods= 0
Subcell Deposition Methods= 0
Advection Scheme= 1
Matrix Solver= 0
Implicit Weighting Factor= 1
Maximum Outer Loop Convergence Iterations= 5
Convergence Maximum Absolute= 0.001
Convergence RMSE= 0.0001
Grain Fractions Max Abs Error= 0.001
Max Subgrid Regions= 1
Max Subgrid Length Scale= 3.402823E+38
Initial Layer Thickness= 3.402823E+38
Min Layer Thickness= 3.402823E+38
Max Layer Thickness= 3.402823E+38
Number of Layers= 5

--- ISNERCK_L.f01 (steady flow) ---

Flow Title=Flow
Program Version=6.20
Number of Profiles= 1
Profile Names=P100yr
River Rch & RM=ISNERCK_L,Main            ,13618
     982
River Rch & RM=ISNERCK_L,Main            ,6302
    1120
River Rch & RM=ISNERCK_L,Main            ,4891
    1500
Boundary for River Rch & Prof#=ISNERCK_L,Main            , 1
Up Type= 0
Dn Type= 3
Dn Slope=0.00432
DSS Import GetInterval= 0
DSS Import GetPeak= 0
DSS Import FillOption= 0

--- ISNERCK_L.g01 (geometry) ---

Geom Title=Geometry
Program Version=6.20

River Reach=ISNERCK_L       ,Main
Reach XY= 30
     2304546.256      699982.538     2304218.347      699655.836
     2304200.307      699425.339     2303700.972      698773.366
     2303755.781      698455.315     2303582.751      698382.251
     2303635.085      698212.188     2303404.636      697831.651
2303396.59452978697571.7211872832303259.23602866 697397.46040228
2303111.62689313 697466.13965284     2302937.031      697312.086
     2302740.687      696903.374     2302508.906      696752.711
     2302375.818      695893.651     2302213.249      695667.799
     2301458.843      695191.226     2301052.135       695239.17
     2300434.942      694823.026     2300207.864      694828.753
     2299694.931      694390.345     2299101.428      694311.295
     2298699.708      693882.366     2298302.259         693713.
     2297907.556      693253.603      2297481.08      693057.638
     2297177.231      692985.399     2296707.864      693186.044
     2295806.302      693183.961     2295487.069      693007.444

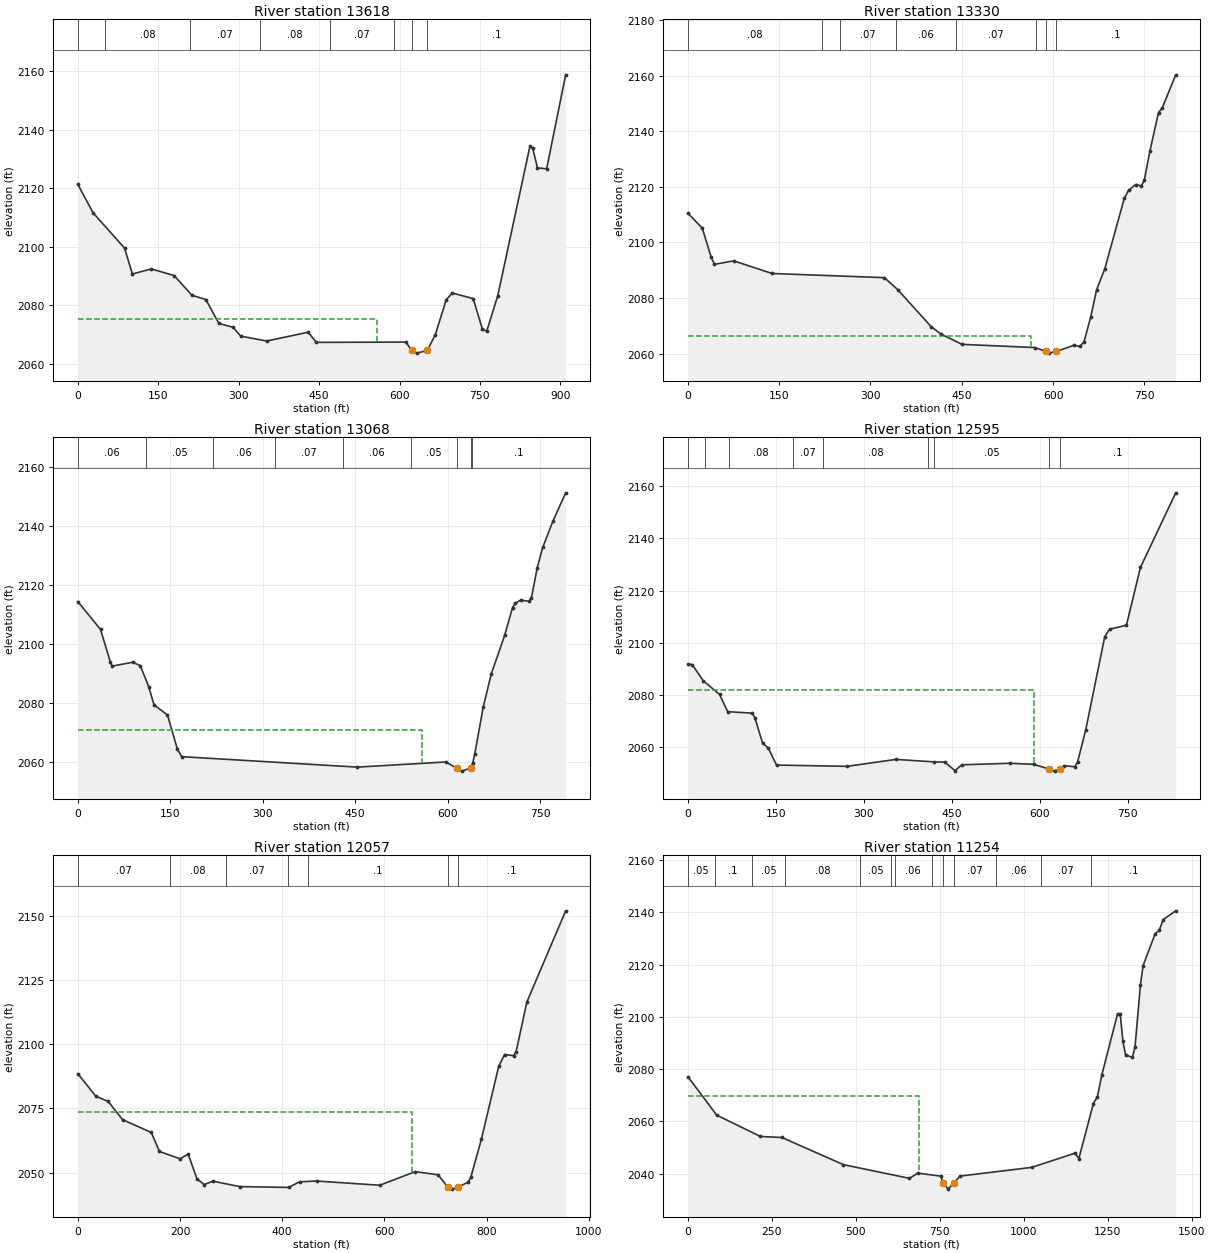
Type RM Length L Ch R = 1 ,13618   ,285.2,288.1,285.5
XS GIS Cut Line= 2
2305040.90855832699591.7251013272304319.45363373700146.106253908
#Sta/Elev= 30
       0 2121.34    28.6 2111.57    87.1 2099.56   101.8 2090.66   137.1  2092.4
   179.6 2090.13   212.8 2083.39   238.7 2081.93   263.2 2073.73   289.7 2072.41
   303.9 2069.38   352.4 2067.73   429.7 2070.74   444.8 2067.26     612 2067.36
  622.392064.503     632 2063.58   651.9 2064.49   666.8 2069.94     687 2081.78
   698.3 2084.14   737.4 2082.26   754.6 2071.75   762.7  2071.1   783.2 2083.23
   843.1  2134.3   848.4 2133.67   857.3 2126.97   874.4 2126.68   909.9 2158.83
#Mann= 8 ,-1,0
       0     .07       0      50     .08       0     210     .07       0
     340     .08       0     470     .07       0     590      .1       0
  622.39    .045       0   651.9      .1       0
#XS Ineff= 2 , 0
          558.07 2075.25
Permanent Ineff=
       F       F
Bank Sta=622.39,651.9
XS Rating Curve= 0 ,0
Exp/Cntr(USF)=0,0
Exp/Cntr=0.3,0.1

Type RM Length L Ch R = 1 ,13330   ,260.3,262.1,264.1
XS GIS Cut Line= 4
2304850.83181413699474.9751095822304588.50988563699660.355434527
 2304242.3266557699856.629682753 2304171.9803346699899.457649904
#Sta/Elev= 30
       0 2110.53    23.6 2105.18    38.5 2094.63    43.7 2092.14    75.2 2093.39
   138.4 2088.85   322.9 2087.35   344.6 2083.08   399.8 2069.72     416 2067.05
   450.3 2063.37   569.9 2062.22   588.3 2060.84   592.9 2060.21  605.292060.826
   634.3 2063.02   643.5 2062.62   650.7 2064.19   661.9 2073.23   671.6 2083.06
   684.9  2090.5     717 2115.85     724 2118.75   735.7 2120.85   745.1 2120.36
   749.8  2122.3     759 2132.81   773.2 2146.71   779.3 2148.37   801.5 2160.29
#Mann= 8 ,-1,0
       0     .08       0     220     .06       0     250     .07       0
  341.21     .06       0  441.21     .07       0  571.21      .1       0
   588.3    .045       0  605.29      .1       0
#XS Ineff= 2 , 0
          564.04 2066.32
Permanent Ineff=
       F       F
Bank Sta=588.3,605.29
XS Rating Curve= 0 ,0
Exp/Cntr(USF)=0,0
Exp/Cntr=0.3,0.1

Type RM Length L Ch R = 1 ,13068   ,472.3,473.7,469.9
XS GIS Cut Line= 2
2304770.12335151699346.1667927032304041.02269731699654.780826228
#Sta/Elev= 30
       0 2114.43    36.9 2104.98    52.6 2094.04    55.7 2092.57      89 2093.87
   101.4 2092.74     115 2085.62   123.7 2079.43   145.5 2076.02   161.7  2064.4
   168.6  2061.9   453.8 2058.36   597.2  2060.1   614.6 2058.04   623.1    2057
  637.63 2058.07   640.6  2059.6     644 2062.64     658 2078.77     671 2089.95
   692.7    2103   705.5 2112.42   710.1  2113.9   718.8 2114.92   731.8 2114.54
   736.2 2115.74   745.4 2125.77   754.5  2132.8   770.9 2141.62   791.7 2151.26
#Mann= 9 ,-1,0
       0     .06       0     110     .05       0     220     .06       0
     320     .07       0     430     .06       0     540     .05       0
   614.6    .045       0  637.63     .05       0     640      .1       0
#XS Ineff= 2 , 0
          557.74 2071.06
Permanent Ineff=
       F       F
Bank Sta=614.6,637.63
XS Rating Curve= 0 ,0
Exp/Cntr(USF)=0,0
Exp/Cntr=0.3,0.1

Type RM Length L Ch R = 1 ,12595   ,538.3,538.1,536.7
BEGIN DESCRIPTION:
Disconnected without IFA
END DESCRIPTION:
XS GIS Cut Line= 2
2304530.94747553698917.9648211872303811.49100987699334.593766446
#Sta/Elev= 30
       0 2091.86     7.3 2091.69    26.3 2085.45      54 2080.23    67.9 2073.62
   109.8 2073.05   114.1 2071.38   127.3 2061.61   137.3  2059.6   151.1 2053.15
   271.3 2052.67   354.5 2055.32     420 2054.37   437.7 2054.28   455.2 2051.03
   466.9 2053.25   548.6 2053.84   589.8 2053.43   616.2 2051.56   624.9 2050.83
  633.412051.578   641.1 2052.94   659.6  2052.5   664.2 2054.38   678.1 2066.73
   710.4 2102.32   718.6 2105.22   747.4 2106.75   771.3 2128.93   831.4  2157.5
#Mann= 9 ,-1,0
       0     .08       0      30     .06       0      70     .08       0
     180     .07       0     230     .08       0     410     .03       0
     420     .05       0   616.2    .045       0  633.41      .1       0
#XS Ineff= 2 , 0
          589.89 2081.79
Permanent Ineff=
       F       F
Bank Sta=616.2,633.41
XS Rating Curve= 0 ,0
Exp/Cntr(USF)=0,0
Exp/Cntr=0.3,0.1

Type RM Length L Ch R = 1 ,12057   ,786.5,802.6,797.5
BEGIN DESCRIPTION:
Structure XS 4 Disconnected without IFA
END DESCRIPTION:
XS GIS Cut Line= 3
2304359.28091938698489.7628496712304129.74923195698510.980064475
2303541.45373054698933.395522863
#Sta/Elev= 30
       0 2088.52    35.1 2079.78    59.4 2077.73    87.5 2070.64   143.7 2065.63
   159.8 2058.22     200 2055.37     216  2057.2   233.2 2047.52   247.2 2045.32
   264.7 2046.63   316.6 2044.53   412.6 2044.21   433.9 2046.39   467.5  2046.7
   590.9 2045.05   660.3 2050.35   705.2 2049.11  723.662044.417   731.9 2043.54
   744.6 2044.36   764.3 2046.32   769.2 2048.21   789.8 2062.96   823.7 2091.35
   835.1    2096   852.9 2095.57   857.8 2097.14   878.9 2116.51   954.8 2152.02
#Mann= 7 ,-1,0
       0     .07       0     180     .08       0  290.51     .07       0
  410.51     .05       0  450.51      .1       0  723.66    .045       0
   744.6      .1       0
#XS Ineff= 2 , 0
          654.87 2073.72
Permanent Ineff=
       F       F
Bank Sta=723.66,744.6
XS Rating Curve= 0 ,0
Exp/Cntr(USF)=0,0
Exp/Cntr=0.3,0.1

Type RM Length L Ch R = 1 ,11254   ,116.9,116.7,115.3
BEGIN DESCRIPTION:
Structure XS 3
END DESCRIPTION:
XS GIS Cut Line= 6
2304354.46980556698192.9338763942303985.62062245698330.954861045
2303678.64291521698200.0728928422303371.66520797698238.147647228
2303262.20028911698309.5378117022303257.44094481698590.339125301
#Sta/Elev= 30
       0  2077.1    85.9 2062.36     216 2054.19   280.1 2053.79   462.9  2043.4
   659.6 2038.15   684.9 2040.16   752.5 2038.99   760.6 2036.39   775.1 2034.02
   791.1 2036.34   811.1 2039.02  1023.9 2042.35  1152.7 2047.78  1164.2 2045.71
  1207.4 2066.79  1219.4 2069.41  1232.4 2077.67  1279.4 2101.16  1287.4    2101
  1295.4 2090.56  1303.2 2085.47  1323.4 2084.43  1331.4 2088.44  1347.4 2112.03
  1355.4 2119.61  1391.4 2131.84  1403.4 2133.07  1415.4 2137.25  1452.6 2140.58
#Mann= 13 ,-1,0
       0     .05       0      80      .1       0     190     .05       0
     290     .08       0  513.83     .05       0  605.82     .07       0
  615.82     .06       0  725.82     .07       0   760.6    .045       0
   791.1     .07       0  918.04     .06       0 1051.03     .07       0
 1201.71      .1       0
#XS Ineff= 2 , 0
          687.36 2069.72
Permanent Ineff=
       F       F
Bank Sta=760.6,791.1
XS Rating Curve= 0 ,0
Exp/Cntr(USF)=0,0
Exp/Cntr=0.3,0.1

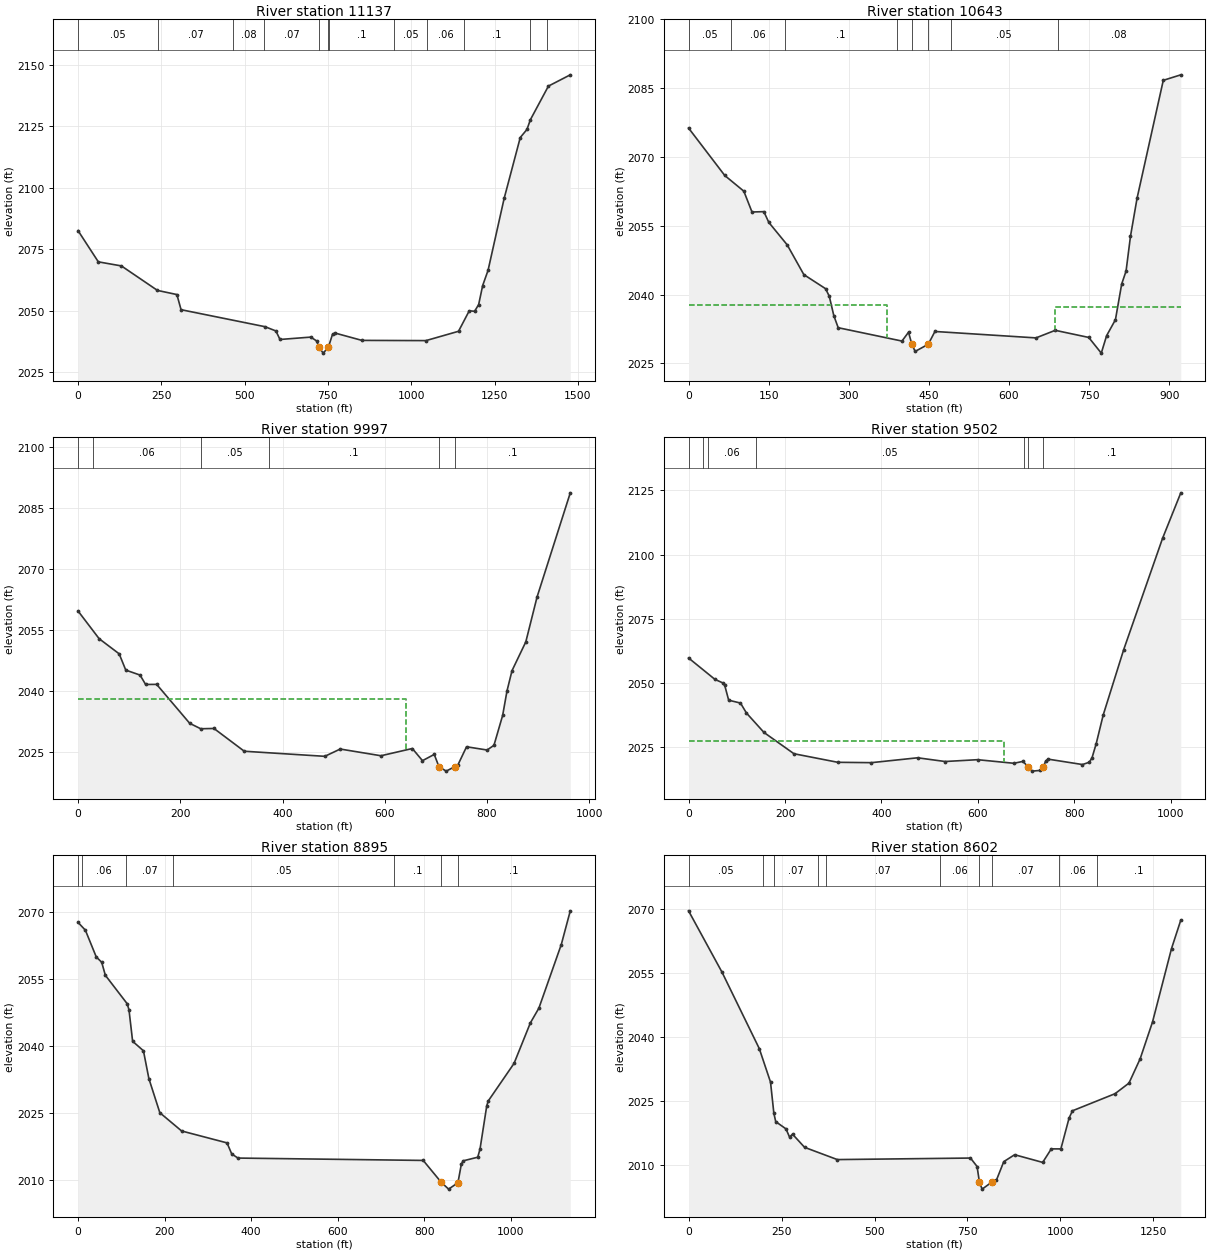
Type RM Length L Ch R = 1 ,11137   ,494.3,494,489.9
BEGIN DESCRIPTION:
Structure XS 2
END DESCRIPTION:
XS GIS Cut Line= 6
2304309.25603473 698066.811252492303938.02717946698173.896499201
2303666.74455446698085.8486296832303402.60094591698104.886006876
2303226.50520687698173.896499201 2302879.0730731698133.442072666
#Sta/Elev= 30
       0  2082.5    60.9  2069.8   130.2 2068.14   238.4 2058.18   296.7  2056.5
   309.2 2050.34   561.1 2043.43   593.9 2041.69   606.1 2038.23   698.6  2039.2
   715.7 2037.66   723.7    2035   735.7 2032.68  751.272035.032   763.7 2040.32
   771.7 2040.83     852 2037.86  1044.1 2037.77  1141.9 2041.56  1174.1  2049.9
  1190.2 2049.69  1202.3 2052.43  1214.4 2060.18  1230.5 2066.32  1278.8 2095.58
  1327.2 2120.36  1347.3 2123.64  1357.5 2127.58  1411.7 2141.27  1477.3 2145.85
#Mann= 12 ,-1,0
       0     .05       0     240     .07       0  466.37     .08       0
  556.99     .07       0   723.7    .045       0  751.27     .07       0
  753.08      .1       0  948.36     .05       0 1048.36     .06       0
  1157.5      .1       0  1357.5     .06       0  1407.5      .1       0
Bank Sta=723.7,751.27
XS Rating Curve= 0 ,0
Exp/Cntr(USF)=0,0
Exp/Cntr=0.3,0.1

Type RM Length L Ch R = 1 ,10643   ,648.9,646.1,632.6
BEGIN DESCRIPTION:
Structure XS 1
END DESCRIPTION:
XS GIS Cut Line= 3
2303855.85427719697556.2053982572303601.24769954697648.789608315
2302968.58893081697801.167787368
#Sta/Elev= 30
       0  2076.3    67.8 2065.96   103.5 2062.54   118.8    2058     141 2058.08
   150.3 2055.73   184.7 2050.84   215.9 2044.35   256.5 2041.29   263.5 2039.64
     272 2035.41   280.2 2032.78   399.6 2029.87   411.9  2031.8     418  2029.2
   424.3 2027.61   448.9 2029.18   461.3 2031.96   650.5 2030.56   686.6 2032.21
   749.3 2030.66   772.8 2027.24   782.8 2031.05   799.3 2034.52     811  2042.3
   819.2 2045.12   827.5 2052.72   839.8    2061   888.9  2086.7   921.7  2087.9
#Mann= 8 ,-1,0
       0     .05       0      80     .06       0     180      .1       0
  390.92     .08       0     418    .045       0   448.9     .08       0
  490.92     .05       0  690.92     .08       0
#XS Ineff= 2 , 0
          371.16 2037.81  685.21          2037.4
Permanent Ineff=
       F       F
Bank Sta=418,448.9
XS Rating Curve= 0 ,0
Exp/Cntr(USF)=0,0
Exp/Cntr=0.3,0.1

Type RM Length L Ch R = 1 ,9997    ,489.4,495.3,496.8
XS GIS Cut Line= 3
2303610.89188808696962.1233837212303375.57368752697056.636431488
 2302866.3605322697550.418885128
#Sta/Elev= 30
       0 2059.74    41.3 2052.92    80.5  2049.2    93.4  2045.2   121.3 2043.98
   132.2 2041.67   153.8 2041.69   218.5 2032.11     240 2030.78   265.9 2030.85
   325.2 2025.25   482.7    2024   512.9 2025.79   592.6 2024.14   653.9 2025.92
   673.8 2022.93   696.8 2024.47   706.1 2021.42   720.3 2020.36     737 2021.46
   743.1 2021.89     760 2026.35   800.2 2025.55   813.6 2026.71   830.6 2034.06
   839.1 2040.07   848.9 2045.06   875.9 2052.14   897.9 2063.17   962.9 2088.79
#Mann= 6 ,-1,0
       0      .1       0      30     .06       0     240     .05       0
  373.59      .1       0   706.1    .045       0     737      .1       0
#XS Ineff= 2 , 0
          641.16 2037.98
Permanent Ineff=
       F       F
Bank Sta=706.1,737
XS Rating Curve= 0 ,0
Exp/Cntr(USF)=0,0
Exp/Cntr=0.3,0.1

Type RM Length L Ch R = 1 ,9502    ,597,606.8,609.3
XS GIS Cut Line= 3
2303429.58114339696661.2247010342303219.33783305696705.587968353
2302540.38695929697139.576452998
#Sta/Elev= 30
       0 2059.68    54.6 2051.35    70.9 2049.97      75    2049    83.2 2043.22
   107.7  2042.1     120 2038.23   156.4 2030.64   218.6 2022.34   309.5    2019
   379.1 2018.86     475 2020.76     532 2019.31   599.2 2020.02   674.5 2018.62
   693.4 2019.35  704.46 2017.18   712.4 2015.56   729.5 2015.84   735.3 2017.14
   740.8 2019.57   745.6 2020.23   816.8 2018.13     831 2019.03   836.6 2020.74
   845.3 2026.28   859.8 2037.44   902.2 2062.88   982.9 2106.34  1020.7 2124.07
#Mann= 7 ,-1,0
       0     .05       0      30      .1       0      40     .06       0
     140     .05       0  694.87      .1       0  704.46    .045       0
   735.3      .1       0
#XS Ineff= 2 , 0
          653.12 2027.33
Permanent Ineff=
       F       F
Bank Sta=704.46,735.3
XS Rating Curve= 0 ,0
Exp/Cntr(USF)=0,0
Exp/Cntr=0.3,0.1

Type RM Length L Ch R = 1 ,8895    ,292.1,293.2,300.7
BEGIN DESCRIPTION:
Structure XS 4
END DESCRIPTION:
XS GIS Cut Line= 2
2303300.34901685 696267.741808292302216.34222409696611.074920586
#Sta/Elev= 30
       0 2067.77      17 2066.02    42.1 2060.03    54.7 2058.83    63.1 2055.92
   113.5 2049.55   117.7 2048.19   126.1 2041.13   151.1    2039   163.7 2032.75
     189 2025.12   239.3 2021.03   344.2 2018.36     355 2015.89   369.4 2014.96
   797.4 2014.43   839.3  2009.5   856.1    2008   877.6 2009.44   885.5 2013.61
   889.7 2014.34   923.3 2015.15   928.6 2016.98   944.2  2026.7   947.7 2027.77
  1007.2 2036.17  1044.9 2045.25  1064.6 2048.56  1116.3  2062.8  1137.1 2070.36
#Mann= 7 ,-1,0
       0      .1       0      10     .06       0     110     .07       0
     220     .05       0     730      .1       0   839.3    .045       0
   877.6      .1       0
Bank Sta=839.3,877.6
XS Rating Curve= 0 ,0
Exp/Cntr(USF)=0,0
Exp/Cntr=0.3,0.1

Type RM Length L Ch R = 1 ,8602    ,143.1,146,140.9
BEGIN DESCRIPTION:
Structure XS 3
END DESCRIPTION:
XS GIS Cut Line= 6
2303038.51110709695825.1600879952302900.49012244696008.394843479
2302564.95634941696198.7686154112302322.22979019696241.602714095
2302069.88703858696117.9109277052301954.58444122696252.074236936
#Sta/Elev= 30
       0 2069.48    90.2 2055.07   190.2 2037.21   220.4 2029.36   229.4 2022.06
   234.4  2020.1     262  2018.4   271.5 2016.49   279.6 2017.16     312 2014.08
     400 2011.21   758.1 2011.57   775.8 2009.59  782.292005.857   789.4 2004.29
   815.4 2005.93   827.5 2006.32   847.6 2010.73   876.8 2012.35   952.2 2010.55
   975.4 2013.72  1001.1 2013.71  1023.2 2020.94  1032.3 2022.64  1146.7 2026.64
  1184.2 2029.12  1214.3 2034.82  1247.5 2043.43  1298.6 2060.63  1323.6 2067.31
#Mann= 10 ,-1,0
       0     .05       0     200     .06       0   229.4     .07       0
   349.4     .06       0   369.4     .07       0  675.18     .06       0
  782.29    .045       0   815.4     .07       0  995.62     .06       0
 1098.24      .1       0
Bank Sta=782.29,815.4
XS Rating Curve= 0 ,0
Exp/Cntr(USF)=0,0
Exp/Cntr=0.3,0.1

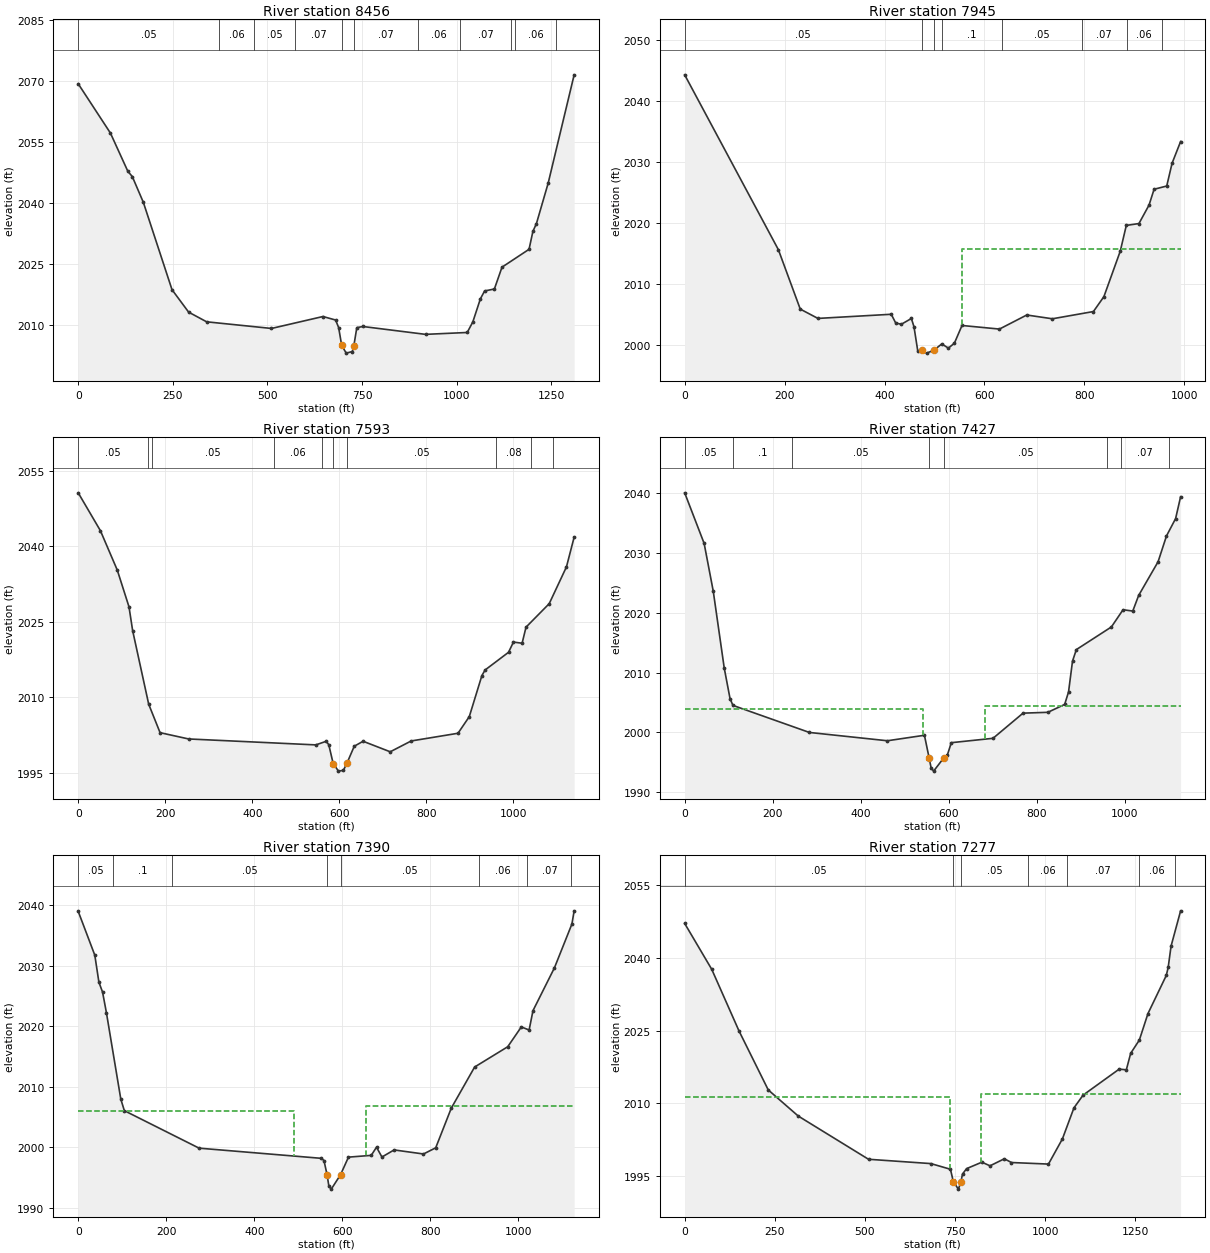
Type RM Length L Ch R = 1 ,8456    ,519.9,510.8,493.3
BEGIN DESCRIPTION:
Structure XS 2
END DESCRIPTION:
XS GIS Cut Line= 6
  2303005.195697695794.2243500562302762.46913779695939.384351154
2302419.79634831696115.4800901912302329.36880664696113.100418042
2302096.11459758695989.3342970642301917.46252108 696214.57581694
#Sta/Elev= 30
       0 2069.24    85.1 2057.14   131.2 2047.74   142.9 2046.46   172.1 2040.13
   247.9 2018.67   291.8 2013.16   339.4 2010.78   510.8 2009.15   646.8 2012.08
   680.3 2011.22   688.3 2009.36   696.3 2004.99   708.3 2003.09   724.3 2003.48
   728.52004.933   736.3 2009.34   752.2 2009.63   917.9  2007.7  1028.1 2008.16
    1043 2010.78  1062.9 2016.43  1074.1 2018.36  1099.9 2018.84    1120  2024.2
  1191.5 2028.59  1201.7    2033    1211  2034.9    1242 2044.82  1310.7 2071.44
#Mann= 11 ,-1,0
       0     .05       0  372.82     .06       0  464.17     .05       0
  574.17     .07       0   696.3    .045       0   728.5     .07       0
  897.63     .06       0 1008.92     .07       0  1143.2      .1       0
  1153.2     .06       0  1263.2      .1       0
Bank Sta=696.3,728.5
XS Rating Curve= 0 ,0
Exp/Cntr(USF)=0,0
Exp/Cntr=0.3,0.1

Type RM Length L Ch R = 1 ,7945    ,345.9,351.8,349.5
BEGIN DESCRIPTION:
Structure XS 1
END DESCRIPTION:
XS GIS Cut Line= 3
2302563.53301181695361.1880848092302376.43575398695444.128106319
 2301894.2263266696067.142686498
#Sta/Elev= 30
       0 2044.34   187.5 2015.63   231.3 2005.87   266.7 2004.34   413.4 2005.02
   422.3 2003.59   433.6 2003.38   453.7 2004.33   458.9 2002.97   466.5 1998.98
   474.1 1999.08   484.2 1998.64  498.65 1999.11   514.5 2000.15   527.8 1999.46
   539.8 2000.28     555 2003.18   629.9 2002.59   684.6  2004.9   735.9 2004.28
     818 2005.47     839 2007.92   871.7 2015.38   883.8 2019.61   909.1 2019.92
   929.3 2022.95   939.4 2025.55   964.7 2026.08   975.4 2029.82   992.5 2033.39
#Mann= 8 ,-1,0
       0     .05       0   474.1    .045       0  498.65     .05       0
  514.66      .1       0  634.66     .05       0  794.66     .07       0
  884.66     .06       0  954.66      .1       0
#XS Ineff= 2 , 0
                          555.14         2015.77
Permanent Ineff=
       F       F
Bank Sta=474.1,498.65
XS Rating Curve= 0 ,0
Exp/Cntr(USF)=0,0
Exp/Cntr=0.3,0.1

Type RM Length L Ch R = 1 ,7593    ,166,166.5,167.5
BEGIN DESCRIPTION:
Structure XS 4
END DESCRIPTION:
XS GIS Cut Line= 2
 2302318.3563074695070.6003493852301553.96506695695915.955148007
#Sta/Elev= 30
       0  2050.6      51 2043.08    89.8 2035.25   116.7 2027.96   125.1 2023.23
     162 2008.61   188.1 2002.97   253.7 2001.72     546 2000.54   569.8 2001.25
   575.8 2000.58   585.9 1996.84   598.1 1995.33   609.4 1995.49  617.461996.884
   634.4 2000.28   654.7 2001.26     717 1999.17   765.2 2001.32   872.8 2002.85
   898.7 2006.15   927.7 2014.31   935.1 2015.42   988.9 2018.93  1000.2 2020.96
  1020.1 2020.73  1029.1 2023.92  1082.4 2028.59    1122 2035.89  1139.7  2041.8
#Mann= 10 ,-1,0
       0     .05       0     160      .1       0     170     .05       0
     450     .06       0     560     .05       0   585.9    .045       0
  617.46     .05       0     960     .08       0    1040     .07       0
    1090      .1       0
Bank Sta=585.9,617.46
XS Rating Curve= 0 ,0
Exp/Cntr(USF)=0,0
Exp/Cntr=0.3,0.1

Type RM Length L Ch R = 1 ,7427    ,35.4,36.2,34.4
XS GIS Cut Line= 6
2302215.02121792695054.6431303882302105.41775455695082.746582535
2301751.31425749695449.4966330522301738.66770403695526.781126457
2301707.75390667695575.9621677142301551.77974725695907.582903048
#Sta/Elev= 30
       0 2040.07    44.2 2031.61    64.9 2023.62    89.9 2010.74     103 2005.66
   109.6 2004.51   283.3 1999.98   460.5 1998.59   544.7 1999.51  555.22 1995.76
   559.9 1994.05   565.5 1993.51   589.1 1995.77   596.7  1996.2   605.8 1998.27
   700.5    1999   768.7 2003.21   825.1 2003.35   863.3 2004.67   872.1 2006.77
   881.1 2011.91   889.8 2013.84   969.4 2017.63   995.9 2020.51    1018 2020.29
  1031.4 2022.91  1075.5 2028.54  1094.6 2032.86  1115.3 2035.76  1126.7 2039.42
#Mann= 8 ,-1,0
       0     .05       0     110      .1       0  243.15     .05       0
  555.22    .045       0   589.1     .05       0  960.28     .06       0
  990.28     .07       0 1100.28      .1       0
#XS Ineff= 2 , 0
          542.31 2003.87   681.3         2004.45
Permanent Ineff=
       F       F
Bank Sta=555.22,589.1
XS Rating Curve= 0 ,0
Exp/Cntr(USF)=0,0
Exp/Cntr=0.3,0.1

Type RM Length L Ch R = 1 ,7390    ,115,113.6,112.1
XS GIS Cut Line= 6
2302189.72811099695032.8629549742302080.12464761695060.966407121
2301726.02115056695427.716457639 2301713.3745971695505.000951043
2301682.46079973  695554.18199232301526.48664032695885.802727634
#Sta/Elev= 30
       0 2038.95    37.7 2031.72      47 2027.26    55.3 2025.63      64 2022.26
    96.8 2007.95   104.8 2006.06   274.7 1999.87   552.7 1998.19   558.3 1997.83
   565.4 1995.48   569.4 1993.63   574.9 1993.11   595.9 1995.48     614 1998.39
   665.7 1998.68   677.7 2000.03     690 1998.41   717.7 1999.58   784.4 1998.91
   812.2 1999.93   847.6 2006.48   900.6 2013.26   975.8 2016.61  1006.7 2019.88
  1024.4 2019.37  1033.2 2022.57  1081.9 2029.63  1121.6 2036.86  1126.7 2039.04
#Mann= 8 ,-1,0
       0     .05       0      80      .1       0  213.15     .05       0
   565.4    .045       0   595.9     .05       0  910.28     .06       0
 1020.28     .07       0 1120.28      .1       0
#XS Ineff= 2 , 0
          490.71 2006.07  653.11         2006.78
Permanent Ineff=
       F       F
Bank Sta=565.4,595.9
XS Rating Curve= 0 ,0
Exp/Cntr(USF)=0,0
Exp/Cntr=0.3,0.1

Type RM Length L Ch R = 1 ,7277    ,78.8,80,81
BEGIN DESCRIPTION:
Structure XS 3
END DESCRIPTION:
XS GIS Cut Line= 4
2302250.83962572694999.4138522422302010.49273866 694975.61713075
2301498.86322659695508.6636921592301498.86322659695903.689268917
#Sta/Elev= 30
       0 2047.06      75 2037.62   150.8  2024.9   231.8 2012.77     315 2007.39
   509.8 1998.49   682.8  1997.6   737.1 1996.43     745 1993.89     759 1992.34
  765.951993.788   770.5 1995.44   781.8 1996.56   824.2 1997.89   846.8 1997.14
   886.5 1998.59   906.3 1997.82  1008.9  1997.5  1047.6 2002.69  1079.6 2009.08
  1104.9  2011.7  1204.9 2017.05  1224.9 2016.92  1236.9 2020.31  1260.9 2023.04
  1284.9 2028.51  1335.6 2036.34  1340.9 2037.99  1348.9 2042.39  1375.4 2049.66
#Mann= 7 ,-1,0
       0     .05       0     745    .045       0  765.95     .05       0
  951.52     .06       0 1060.37     .07       0 1260.37     .06       0
 1360.37      .1       0
#XS Ineff= 2 , 0
          734.87 2011.41  821.81         2011.83
Permanent Ineff=
       F       F
Bank Sta=745,765.95
XS Rating Curve= 0 ,0
Exp/Cntr(USF)=0,0
Exp/Cntr=0.3,0.1

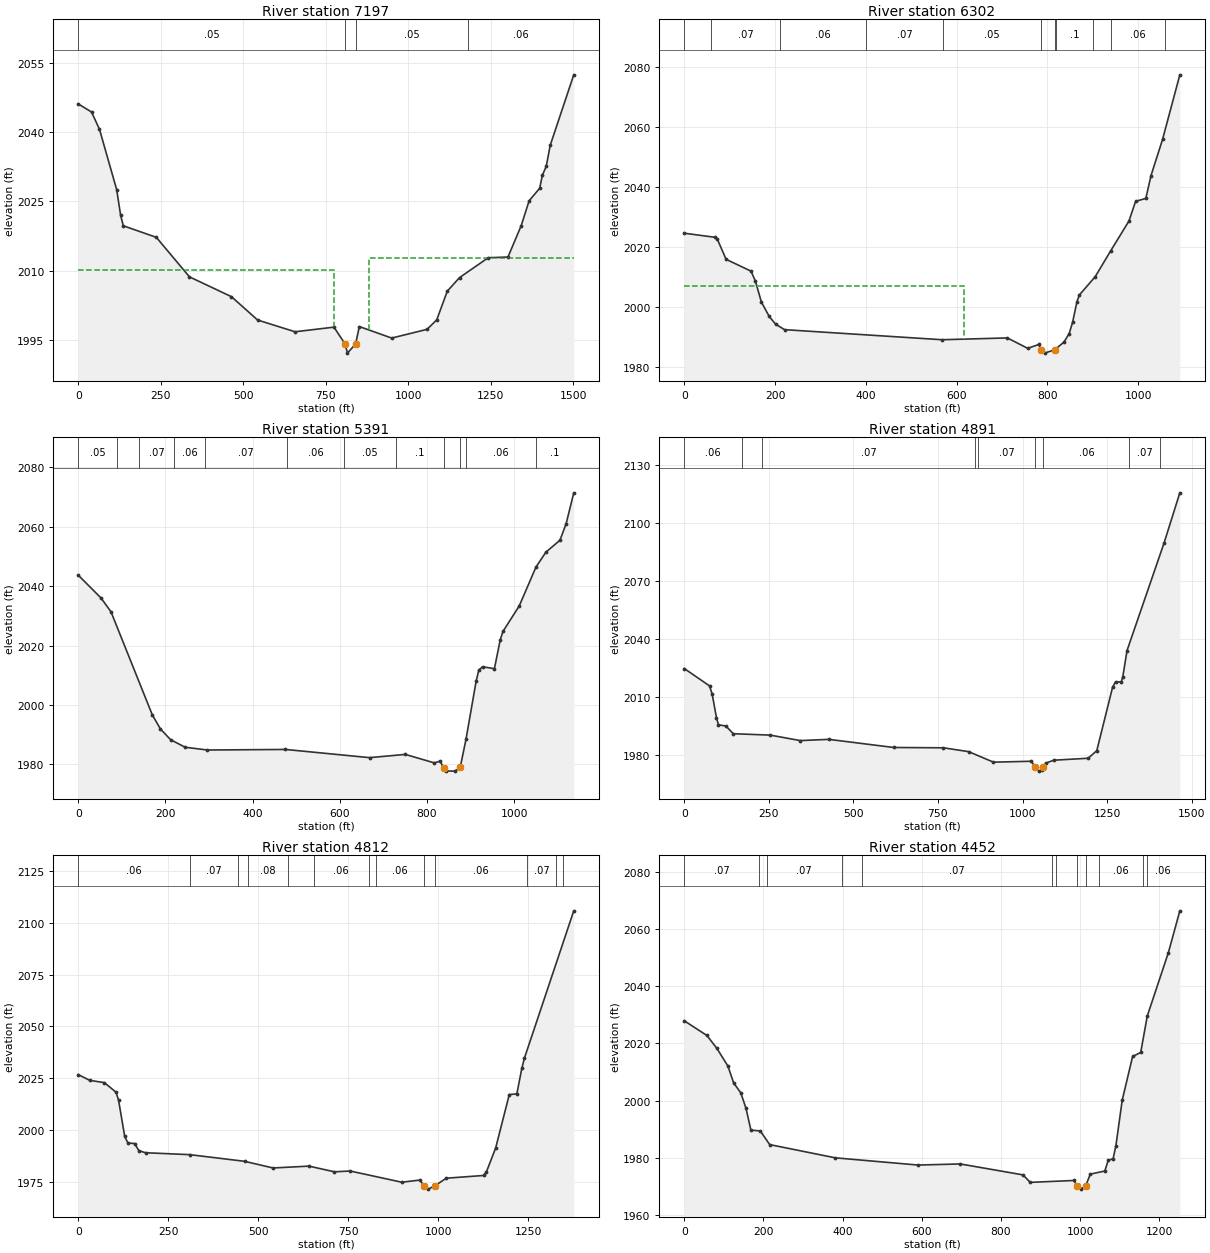
Type RM Length L Ch R = 1 ,7197    ,900,895.2,893.8
BEGIN DESCRIPTION:
Structure XS 2
END DESCRIPTION:
XS GIS Cut Line= 4
2301981.93667287694644.8427020192301998.59437791694889.948933381
2301422.71371782695468.2092656232301425.09338997695908.448613215
#Sta/Elev= 30
       0 2046.19    40.4 2044.43    64.5 2040.67   116.6 2027.58   128.6 2022.01
   136.7 2019.72   236.9  2017.2   337.3 2008.62   464.5 2004.32   543.8 1999.25
   657.2  1996.7   775.2  1997.7   809.1 1994.02     816 1992.06   840.8 1994.05
   852.1 1997.83   950.2 1995.33  1057.5 1997.23  1086.7 1999.29  1118.7 2005.52
  1155.7 2008.46  1242.7 2012.78  1302.6 2012.93  1342.7 2019.74  1366.7 2025.15
  1398.7 2027.86  1406.7 2030.65  1418.7 2032.67  1430.7 2037.21    1502  2052.5
#Mann= 4 ,-1,0
       0     .05       0   809.1    .045       0   840.8     .05       0
 1181.77     .06       0
#XS Ineff= 2 , 0
          775.16 2010.03  880.29         2012.81
Permanent Ineff=
       F       F
Bank Sta=809.1,840.8
XS Rating Curve= 0 ,0
Exp/Cntr(USF)=0,0
Exp/Cntr=0.3,0.1

Type RM Length L Ch R = 1 ,6302    ,900.6,910.3,909.9
BEGIN DESCRIPTION:
Structure XS 1
END DESCRIPTION:
XS GIS Cut Line= 2
2301263.44876996694434.7982895762300618.12158566695315.872305041
#Sta/Elev= 30
       0 2024.56    67.4  2023.2    72.4 2022.73    92.2 2015.85   147.1  2011.9
   156.7 2008.62     170 2001.59   187.2 1996.79   201.3  1994.2   221.1 1992.38
   568.2 1989.02     712 1989.62   756.9 1986.15   781.4 1987.44   786.21985.641
   793.9 1984.55   816.1 1985.64   836.9 1988.25   848.3 1991.09   855.8 1994.84
   865.5 2001.76   870.6 2003.93   905.6 2010.04     940 2018.75     980 2028.63
   994.6 2035.18  1017.2 2036.18  1028.6 2043.79  1054.1 2055.87  1092.1  2077.4
#Mann= 11 ,-1,0
       0     .08       0      60     .07       0     210     .06       0
     400     .07       0     570     .05       0   786.2    .045       0
   816.1     .05       0     820      .1       0     900     .05       0
     940     .06       0    1060      .1       0
#XS Ineff= 2 , 0
           616.9 2007.07
Permanent Ineff=
       F       F
Bank Sta=786.2,816.1
XS Rating Curve= 0 ,0
Exp/Cntr(USF)=0,0
Exp/Cntr=0.3,0.1

Type RM Length L Ch R = 1 ,5391    ,506.5,500.2,495.4
BEGIN DESCRIPTION:
Structure XS 4
END DESCRIPTION:
XS GIS Cut Line= 2
2300701.46642496694120.4691813562299837.06137736694858.666329448
#Sta/Elev= 30
       0 2043.74    52.5 2036.01    75.2 2031.39     170 1996.67   188.7 1991.91
   212.1  1988.3   245.4 1985.77   296.5 1984.84   475.4 1985.03   668.2 1982.27
   750.4 1983.36     817  1980.5   829.9 1981.09   838.1 1978.91   843.3 1977.78
   864.4 1977.73  876.211978.993   889.5 1988.43   912.7 2007.96   918.8 2011.71
   927.5 2012.88   954.7 2012.23   968.1 2021.98   974.3 2024.78  1011.5 2033.32
    1050 2046.45  1072.8 2051.47  1105.1  2055.5  1119.3  2061.1  1136.7 2071.45
#Mann= 12 ,-1,0
       0     .05       0      90     .06       0     140     .07       0
     220     .06       0     290     .07       0     480     .06       0
     610     .05       0     730      .1       0   838.1    .045       0
  876.21      .1       0     890     .06       0    1050      .1       0
Bank Sta=838.1,876.21
XS Rating Curve= 0 ,0
Exp/Cntr(USF)=0,0
Exp/Cntr=0.3,0.1

Type RM Length L Ch R = 1 ,4891    ,78.7,79.2,80.1
BEGIN DESCRIPTION:
Structure XS 3
END DESCRIPTION:
XS GIS Cut Line= 6
2299881.97969477693513.2246506582300049.03267964693879.456194411
2299920.53038359693956.557572044 2299864.8460553694018.667015136
2299622.83339773694432.0160674432299502.89792141 694759.69692238
#Sta/Elev= 30
       0 2024.61    74.7 2015.62    82.4 2011.44    95.2 1999.22   101.1 1995.47
   123.1 1994.85     145 1990.86   254.2 1990.14   342.8 1987.31   427.4 1987.94
   619.1 1983.74   766.1 1983.57   840.6 1981.59   914.2 1976.14  1026.1 1976.61
 1037.811973.513  1048.3  1971.5  1058.1 1971.98 1061.261973.455  1068.9 1975.64
  1092.4 1977.15  1194.2 1978.17  1219.6 1982.08  1266.4 2015.01    1275 2017.63
    1292 2017.71  1296.3 2020.08    1309  2033.9  1418.5 2089.57  1465.1 2115.54
#Mann= 9 ,-1,0
       0     .06       0     170     .08       0     230     .07       0
  859.12     .05       0  869.12     .07       0 1037.81    .045       0
 1061.26     .06       0 1316.12     .07       0 1406.12      .1       0
Bank Sta=1037.81,1061.26
XS Rating Curve= 0 ,0
Exp/Cntr(USF)=0,0
Exp/Cntr=0.3,0.1

Type RM Length L Ch R = 1 ,4812    ,364.5,360.2,354.6
BEGIN DESCRIPTION:
Structure XS 2
END DESCRIPTION:
XS GIS Cut Line= 6
2299804.87831714693530.3582901322299937.66402306693836.622095727
2299822.01195661693913.7234733592299768.46933326694044.367474347
2299539.30690529694423.4492477062299440.78847832694727.571348366
#Sta/Elev= 30
       0 2026.77      32 2023.99    72.8 2022.87     105 2018.27   112.1 2014.45
   129.3 1996.88   138.2 1993.72   156.7 1993.46   168.7 1990.01   187.1 1989.02
     310 1988.09   462.2 1984.88   541.3 1981.66   641.2 1982.55   712.2  1979.8
   755.8 1980.19   899.4 1974.77   949.7 1975.83  961.261972.938   972.5 1971.44
   990.8 1972.99  1022.8 1976.72  1126.5 1978.03  1134.3 1979.74  1160.1 1991.32
  1197.9  2017.1    1219 2017.47  1232.7 2029.71    1240 2034.71  1377.1 2105.86
#Mann= 13 ,-1,0
       0     .06       0     310     .07       0  443.81     .06       0
  472.81     .08       0  582.81     .07       0     654     .06       0
  808.04     .07       0  828.04     .06       0  961.26    .045       0
   990.8     .06       0 1247.37     .07       0 1327.37     .06       0
 1347.37      .1       0
Bank Sta=961.26,990.8
XS Rating Curve= 0 ,0
Exp/Cntr(USF)=0,0
Exp/Cntr=0.3,0.1

Type RM Length L Ch R = 1 ,4452    ,517,528,534.2
BEGIN DESCRIPTION:
Structure XS 1
END DESCRIPTION:
XS GIS Cut Line= 4
2299710.85347784693513.2424950222299575.12045384693594.206053199
2299262.92006746694197.0094736122299168.61240092694601.347436344
#Sta/Elev= 30
       0 2027.89    57.3 2022.75    82.3 2018.27   110.2 2012.11   124.8 2006.19
   142.8 2002.73     156 1997.32   168.4 1989.71   192.1 1989.43   215.9 1984.66
   381.9 1980.03   590.6 1977.52   697.4  1977.9     856 1974.08     874 1971.47
   984.9 1972.13   991.9 1970.28  1002.5 1969.11  1014.31970.302    1026 1974.35
  1062.5 1975.43  1071.2 1979.16  1083.5 1979.74  1090.6 1984.28  1106.6 2000.21
  1132.8 2015.42  1153.3 2016.84  1169.8 2029.53  1223.2 2051.69  1252.1 2066.28
#Mann= 12 ,-1,0
       0     .07       0  188.05     .08       0  208.05     .07       0
  398.05     .06       0  448.05     .07       0  928.05     .06       0
  938.05     .07       0   991.9    .045       0  1014.3     .07       0
 1048.05     .06       0 1158.05      .1       0 1168.05     .06       0
Bank Sta=991.9,1014.3
XS Rating Curve= 0 ,0
Exp/Cntr(USF)=0,0
Exp/Cntr=0.3,0.1