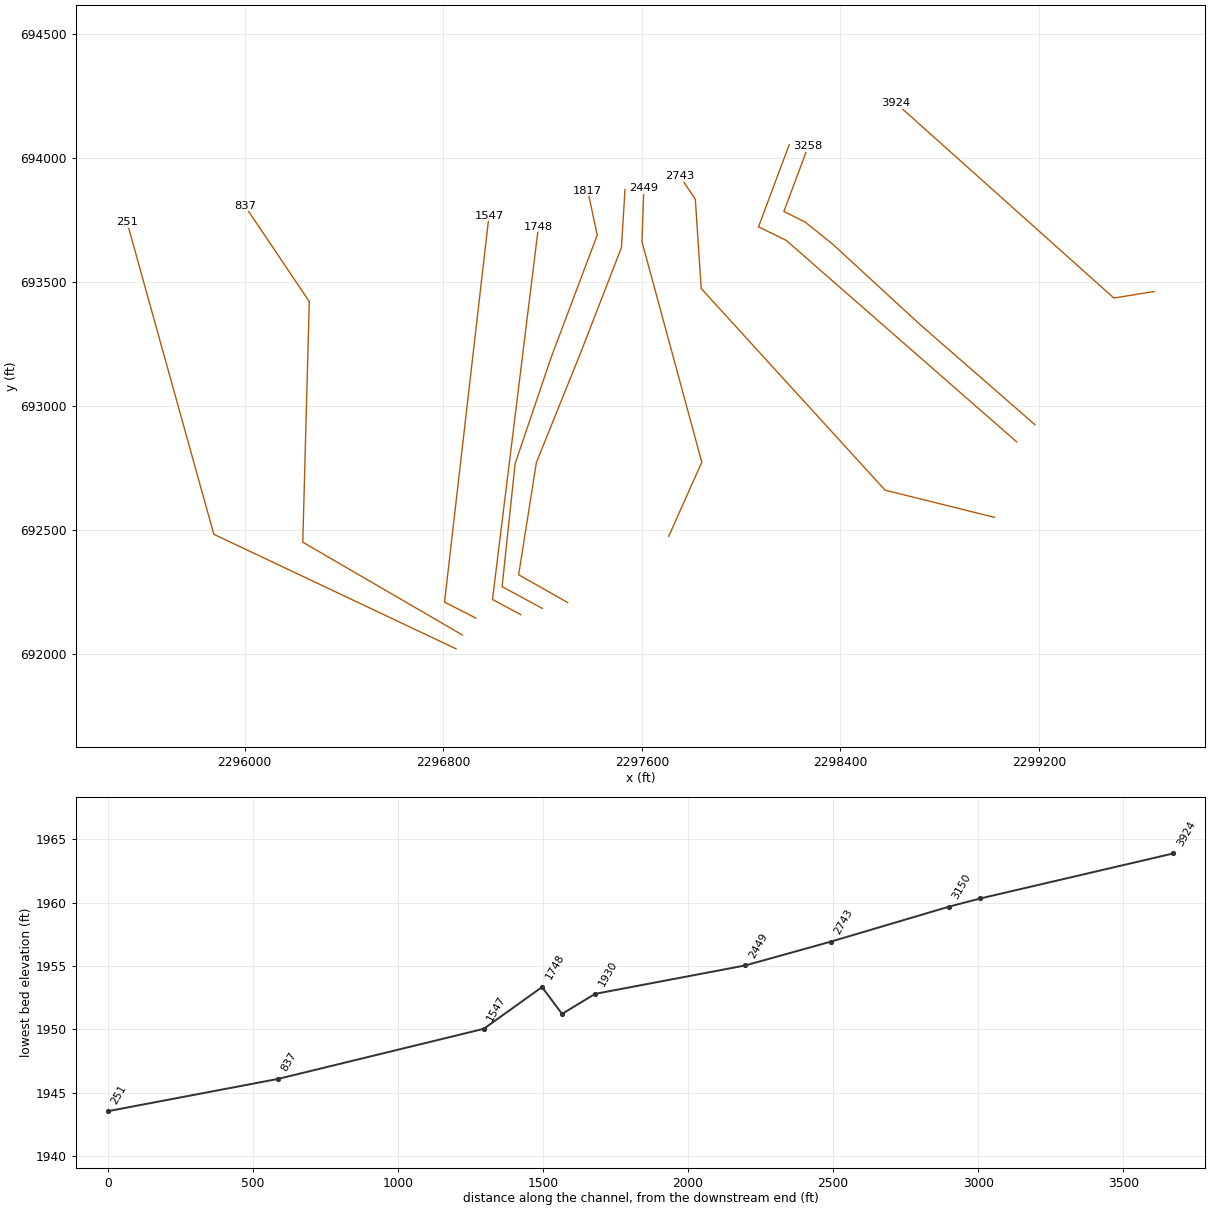
HEC-RAS study ISNERCK_L.prj: ISNERCK_L

--- ISNERCK_L.g01 (geometry) --- (continued)

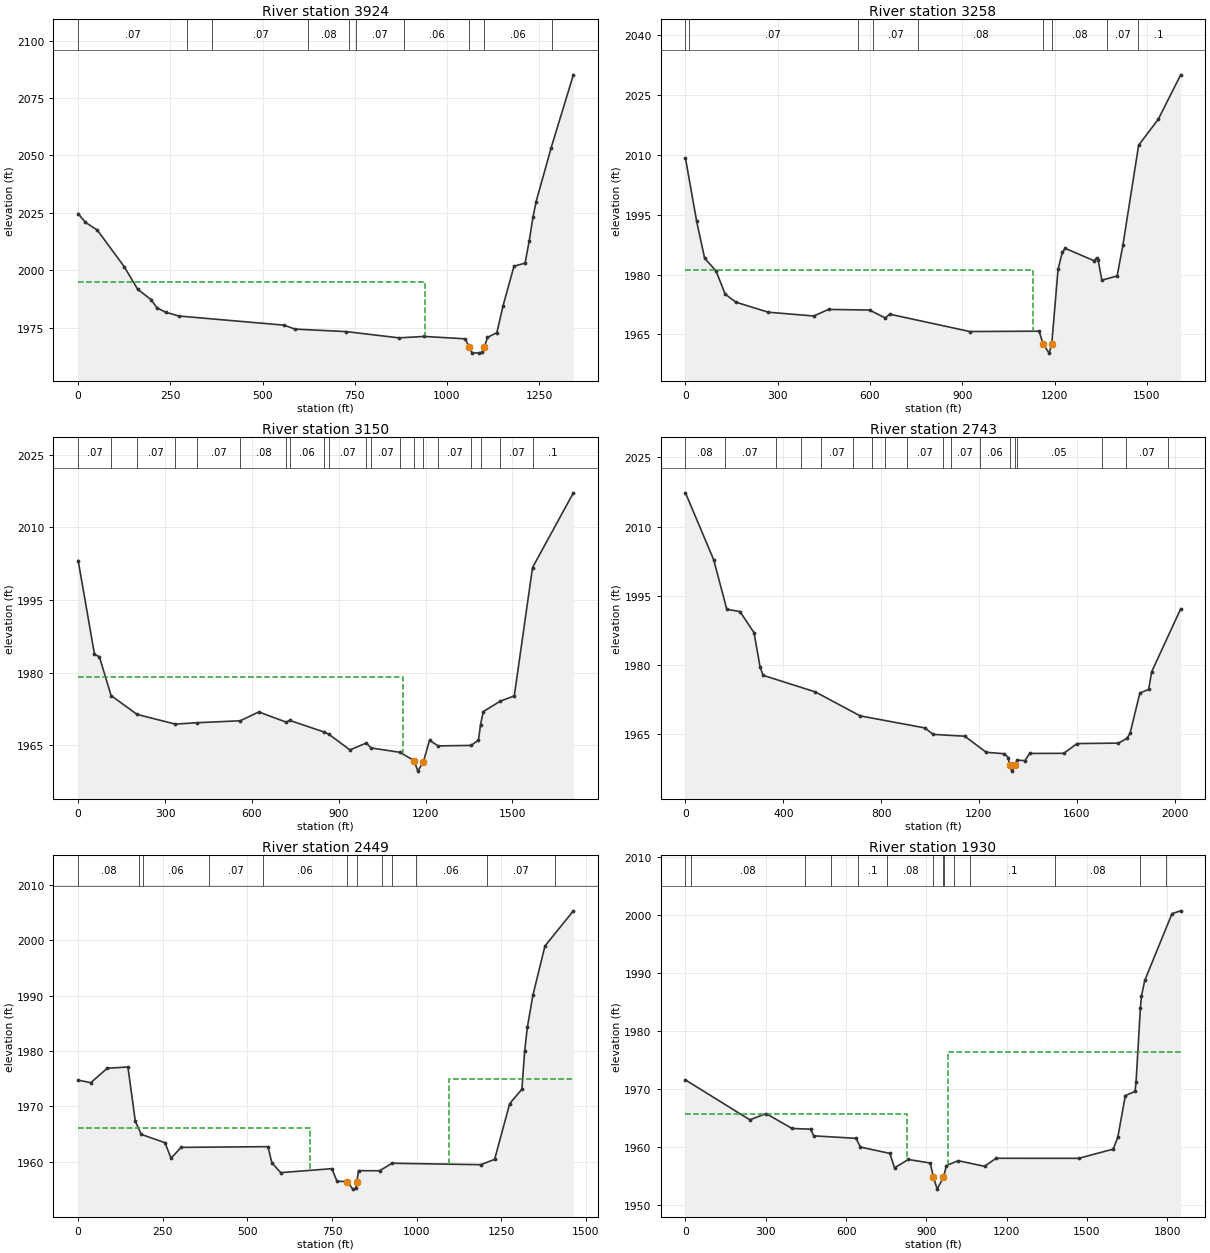
Type RM Length L Ch R = 1 ,3924    ,663.5,665.7,661.8
BEGIN DESCRIPTION:
Structure XS 4
END DESCRIPTION:
XS GIS Cut Line= 3
2299663.22785539693460.8543103182299501.30073903693434.660217967
2298622.60800469694220.482988517
#Sta/Elev= 30
       0 2024.65    19.3 2020.87    51.7  2017.5   124.7 2001.58   161.1 1991.75
   197.8 1987.18   213.8 1983.58   237.4 1981.71   272.9 1980.05   557.8 1976.08
   587.8 1974.36   727.5 1973.26   869.9 1970.54   938.3 1971.16  1049.9 1970.12
 1060.38  1966.4  1067.9 1964.11  1085.9 1963.89  1095.8  1964.3 1101.451966.506
    1110 1970.74  1135.4  1972.8  1151.9 1984.33  1181.9 2001.75    1212 2003.09
  1223.3  2012.9  1233.4 2023.16  1241.9 2029.89  1282.7 2053.34  1342.9 2085.08
#Mann= 10 ,-1,0
       0     .07       0  294.03     .08       0  364.03     .07       0
  624.03     .08       0  734.03     .06       0  754.03     .07       0
  884.03     .06       0 1060.38    .045       0 1101.45     .06       0
 1284.03      .1       0
#XS Ineff= 2 , 0
          941.08    1995
Permanent Ineff=
       F       F
Bank Sta=1060.38,1101.45
XS Rating Curve= 0 ,0
Exp/Cntr(USF)=0,0
Exp/Cntr=0.3,0.1

Type RM Length L Ch R = 1 ,3258    ,109.2,108.2,108.3
BEGIN DESCRIPTION:
Structure XS 3
END DESCRIPTION:
XS GIS Cut Line= 6
2299183.56876385692924.3205208272298719.53269477693328.864786182
2298364.96154454693654.8798706152298257.87629783693740.548067984
2298172.20810046693783.3821666682298269.77465858694045.146103074
#Sta/Elev= 30
       0 2009.17    36.3 1993.38    62.2 1984.13    99.4  1980.9   129.1 1975.11
   163.7  1973.1   269.1 1970.58   416.9 1969.63   465.1 1971.28   598.4 1971.12
   649.4 1969.14   663.7 1970.09   924.5 1965.74  1149.5 1965.83  1162.1  1962.7
    1182 1960.33  1190.6 1962.57  1190.6 1962.62    1211 1981.28  1224.7 1985.57
  1234.4 1986.58  1328.6 1983.46  1336.4  1984.2  1341.6 1983.55  1353.5  1978.6
  1403.1 1979.66  1421.8 1987.34    1473 2012.41    1537 2018.93  1609.6 2030.04
#Mann= 9 ,-1,0
       0     .06       0      10     .07       0     560     .08       0
     610     .07       0  755.62     .08       0  1162.1    .045       0
  1190.6     .08       0  1370.2     .07       0  1470.2      .1       0
#XS Ineff= 2 , 0
         1129.39  1981.1
Permanent Ineff=
       F       F
Bank Sta=1162.1,1190.6
XS Rating Curve= 0 ,0
Exp/Cntr(USF)=0,0
Exp/Cntr=0.3,0.1

Type RM Length L Ch R = 1 ,3150    ,407.5,406.6,405.7
BEGIN DESCRIPTION:
Structure XS 2
END DESCRIPTION:
XS GIS Cut Line= 5
2299109.79892723692855.3100285022298372.10056099 693500.20118092
2298181.72678906 693666.778231362298069.88219805693721.510690791
2298193.62514981694052.285119522
#Sta/Elev= 30
       0 2003.15    56.3 1983.82    73.3 1983.28   113.7 1975.28   203.4 1971.39
   335.3 1969.39     410 1969.67     560 1970.08   623.8  1971.9   719.4 1969.78
     730 1970.16   850.1 1967.75   865.9  1967.3   938.8 1964.06   995.7  1965.5
  1011.2 1964.47  1110.9 1963.57  1160.5 1961.85  1173.2 1959.68 1192.681961.646
  1213.6 1966.04  1243.4 1964.89  1357.3 1964.99  1382.6 1966.06  1389.9 1969.28
  1399.2 1971.96  1458.3 1974.14  1506.4  1975.2  1569.4 2001.71  1710.5 2017.14
#Mann= 20 ,-1,0
       0     .07       0   113.7     .08       0   203.4     .07       0
   335.3     .06       0     410     .07       0     560     .08       0
   719.4     .07       0     730     .06       0   850.1     .05       0
   865.9     .07       0   995.7     .06       0  1011.2     .07       0
  1110.9     .06       0  1160.5    .045       0 1192.68     .08       0
  1243.4     .07       0  1357.3     .07       0  1389.9     .08       0
  1458.3     .07       0  1569.4      .1       0
#XS Ineff= 2 , 0
         1120.29 1979.21
Permanent Ineff=
       F       F
Bank Sta=1160.5,1192.68
XS Rating Curve= 0 ,0
Exp/Cntr(USF)=0,0
Exp/Cntr=0.3,0.1

Type RM Length L Ch R = 1 ,2743    ,299.4,294.7,289.7
BEGIN DESCRIPTION:
Structure XS 1
END DESCRIPTION:
XS GIS Cut Line= 5
2299020.28195221692551.2049213782298579.74494448692660.743853031
2297839.16651526693472.7607159332297815.35370403693832.334165487
2297753.44039484 693925.20412928
#Sta/Elev= 30
       0 2017.32   115.5 2002.78   169.1 1992.03   222.7 1991.56   280.4 1986.97
   305.1 1979.52   317.5 1977.71   530.3 1974.13   714.5 1968.91   979.7 1966.29
  1012.2  1964.9  1141.9  1964.5  1229.8 1961.01  1303.4  1960.7    1320 1959.86
  1325.21958.214  1334.5 1956.92  1348.7 1958.23  1355.6 1959.32  1388.3 1959.19
  1407.4 1960.76  1546.9 1960.78  1601.3  1962.9  1770.5    1963  1805.9 1964.04
    1818 1965.13    1858 1973.85  1894.1 1974.67  1906.2 1978.46  2024.9 1992.13
#Mann= 18 ,-1,0
       0     .08       0     160     .07       0     370     .08       0
  473.95     .06       0  553.95     .07       0  683.95     .08       0
  763.95     .07       0  813.95     .08       0  903.95     .07       0
 1053.95     .06       0 1083.95     .07       0 1203.95     .06       0
  1325.2    .045       0  1348.7     .06       0 1353.95     .05       0
 1702.96     .06       0 1802.96     .07       0 1973.32     .06       0
Bank Sta=1325.2,1348.7
XS Rating Curve= 0 ,0
Exp/Cntr(USF)=0,0
Exp/Cntr=0.3,0.1

Type RM Length L Ch R = 1 ,2449    ,525.9,518.2,503.3
BEGIN DESCRIPTION:
Disconnected without IFA
END DESCRIPTION:
XS GIS Cut Line= 4
 2297708.1960535692475.0039254462297841.41861024692773.363562567
 2297600.3255147 693661.955588332297607.96168411693877.099572295
#Sta/Elev= 30
       0 1974.74    37.4 1974.29    85.6 1976.89   146.9 1977.13   168.8 1967.31
   186.4 1964.94   256.5 1963.43   274.2 1960.63   304.1 1962.59   560.6 1962.72
   572.1 1959.81   598.2 1958.02   749.3 1958.74   764.5 1956.47  793.691956.401
   811.5 1955.04   819.8 1955.16   823.1 1956.39   828.1 1958.38   890.2 1958.36
   927.3 1959.72  1189.3 1959.46  1230.1 1960.42  1274.7 1970.51  1310.7 1973.11
  1318.7 1979.93  1326.7 1984.27  1343.2 1990.11  1378.8    1999  1462.7 2005.36
#Mann= 12 ,-1,0
       0     .08       0     180     .07       0     190     .06       0
  386.75     .07       0  546.75     .06       0  793.69    .045       0
   823.1     .07       0  896.75     .06       0  926.75     .07       0
  996.75     .06       0 1206.75     .07       0 1407.47     .06       0
#XS Ineff= 2 , 0
          685.65 1966.06 1093.89         1975.03
Permanent Ineff=
       F       F
Bank Sta=793.69,823.1
XS Rating Curve= 0 ,0
Exp/Cntr(USF)=0,0
Exp/Cntr=0.3,0.1

Type RM Length L Ch R = 1 ,1930    ,114,113.6,118.1
BEGIN DESCRIPTION:
Structure XS 3
END DESCRIPTION:
XS GIS Cut Line= 6
2297301.24809388692208.039203935 2297103.7353055692319.883794945
2297175.12546997692772.0215032822297353.60088116693214.640523023
2297517.79825945693638.2221655712297532.07629234693871.430036187
#Sta/Elev= 30
       0 1971.62   240.4 1964.74   301.1 1965.82   398.3 1963.25   467.1 1963.13
   479.2 1961.98   637.3 1961.55   653.5 1960.04   763.6 1958.95   780.9 1956.46
   832.6  1957.9   914.6 1957.29   926.2 1954.86   940.4 1952.79  963.891954.874
   974.9 1956.86  1019.1 1957.69  1117.3 1956.72  1160.4 1958.11  1468.9  1958.1
    1598 1959.69  1615.1 1961.75  1643.3 1968.92  1679.3 1969.64  1683.3 1971.25
  1699.4 1983.94  1703.4 1986.08  1715.7 1988.77  1817.7  2000.3  1849.9 2000.78
#Mann= 14 ,-1,0
       0      .1       0      20     .08       0  446.98     .07       0
  543.15     .08       0  643.15      .1       0  754.73     .08       0
   926.2    .045       0  963.89     .08       0  964.73     .07       0
 1004.73     .08       0 1064.73      .1       0 1381.97     .08       0
 1696.27     .07       0 1796.27     .06       0
#XS Ineff= 2 , 0
          827.76 1965.71  981.95         1976.38
Permanent Ineff=
       F       F
Bank Sta=926.2,963.89
XS Rating Curve= 0 ,0
Exp/Cntr(USF)=0,0
Exp/Cntr=0.3,0.1

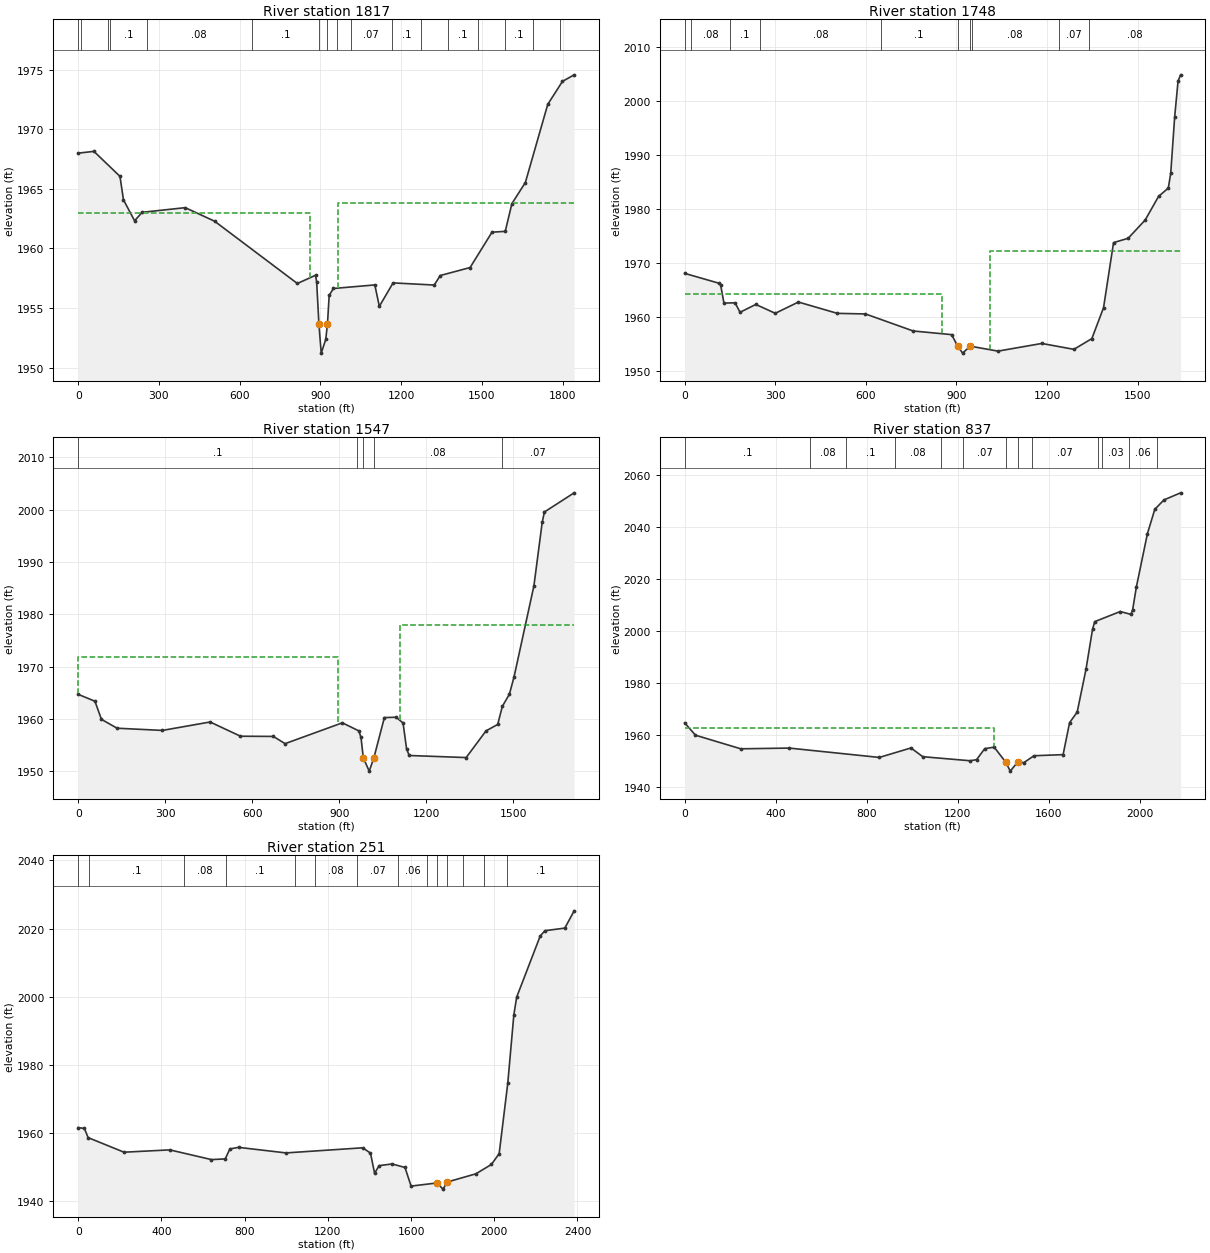
Type RM Length L Ch R = 1 ,1817    ,65.8,69.1,75.1
BEGIN DESCRIPTION:
Structure XS 2
END DESCRIPTION:
XS GIS Cut Line= 6
2297198.92219146692184.2424824442297037.10448532692272.290351962
 2297089.4572726692767.262158984 2297234.6172737 693195.60314583
2297420.23170133693688.1952807032297382.15694695693866.670691888
#Sta/Elev= 30
       0 1968.01    58.4 1968.16   155.2 1966.06   168.2 1964.09   209.5 1962.33
   237.6 1963.04   397.9 1963.43   507.1 1962.29   814.5 1957.06     882 1957.75
   886.2 1957.21   894.7 1953.63   903.2 1951.21   920.1 1952.37   926.5 1953.68
   932.8 1956.06   948.4 1956.64  1102.4 1956.94  1119.2 1955.14  1170.3 1957.11
  1323.2 1956.93  1345.6 1957.73  1456.5  1958.4  1537.9 1961.37  1587.2 1961.44
  1611.9 1963.77  1661.9 1965.54  1745.2 1972.11  1799.9 1974.04  1843.3 1974.59
#Mann= 17 ,-1,0
       0     .08       0      10      .1       0     110     .08       0
     120      .1       0  254.43     .08       0  644.43      .1       0
   894.7    .045       0   926.5      .1       0  962.24     .08       0
 1012.24     .07       0 1164.46      .1       0 1274.46     .08       0
 1374.46      .1       0 1484.46     .08       0 1584.46      .1       0
 1690.86     .08       0 1790.86     .07       0
#XS Ineff= 2 , 0
          859.98 1962.96  966.07         1963.79
Permanent Ineff=
       F       F
Bank Sta=894.7,926.5
XS Rating Curve= 0 ,0
Exp/Cntr(USF)=0,0
Exp/Cntr=0.3,0.1

Type RM Length L Ch R = 1 ,1748    ,200.2,200.9,199.6
BEGIN DESCRIPTION:
Structure XS 3
END DESCRIPTION:
XS GIS Cut Line= 3
2297112.91496531 692158.764042112296998.33815813692220.459245977
2297183.42376973693721.709206733
#Sta/Elev= 30
       0 1968.09   114.5 1966.25     119 1965.98   130.1 1962.59   167.1 1962.64
   183.3 1960.89   235.6 1962.34   300.1  1960.7   376.7 1962.78   505.6 1960.69
   598.9 1960.58   756.7 1957.43   884.5 1956.75   903.8 1954.63   920.8 1953.33
  945.68 1954.62  1037.7  1953.7  1182.8 1955.12  1289.3 1954.03  1348.7 1956.02
  1387.4 1961.73  1420.5 1973.78  1468.9 1974.58  1525.3 1977.96  1569.7 1982.34
  1601.9 1983.87    1610 1986.64  1622.9 1996.97  1634.2 2003.68  1642.7 2004.83
#Mann= 10 ,-1,0
       0      .1       0      20     .08       0  150.13      .1       0
  250.13     .08       0  650.13      .1       0   903.8    .045       0
  945.68      .1       0  950.13     .08       0 1240.13     .07       0
 1340.13     .08       0
#XS Ineff= 2 , 0
          852.01  1964.2 1012.42         1972.14
Permanent Ineff=
       F       F
Bank Sta=903.8,945.68
XS Rating Curve= 0 ,0
Exp/Cntr(USF)=0,0
Exp/Cntr=0.3,0.1

Type RM Length L Ch R = 1 ,1547    ,706,709.4,707.3
BEGIN DESCRIPTION:
Structure XS 2
END DESCRIPTION:
XS GIS Cut Line= 3
2296931.43838278692145.212897668 2296805.1101082692209.845968386
 2296984.3199861693766.915399306
#Sta/Elev= 30
       0  1964.7    57.6 1963.39      80 1959.93     134 1958.23   290.2 1957.81
   454.6 1959.42   559.3  1956.7   672.7 1956.66     713 1955.28   910.3 1959.26
   967.3 1957.72   974.6 1956.46   982.7 1952.56  1002.9 1950.03    1019 1952.56
  1055.2 1960.26  1095.5 1960.33  1119.6 1959.23  1131.7 1954.32  1140.7 1953.02
  1337.1 1952.62  1405.5 1957.72  1445.8 1958.95  1461.9 1962.42  1486.1 1964.73
  1502.2 1968.05  1570.6 1985.43  1599.2 1997.57  1606.8 1999.55  1709.3 2003.21
#Mann= 5 ,-1,0
       0      .1       0   961.9     .08       0   982.7    .045       0
    1019     .08       0  1461.9     .07       0
#XS Ineff= 2 , 0
          894.42  1971.8 1108.59         1978.03
Permanent Ineff=
       F       F
Bank Sta=982.7,1019
XS Rating Curve= 0 ,0
Exp/Cntr(USF)=0,0
Exp/Cntr=0.3,0.1

Type RM Length L Ch R = 1 ,837     ,576.1,586.6,589.1
BEGIN DESCRIPTION:
Structure XS 1
END DESCRIPTION:
XS GIS Cut Line= 4
2296877.12894162692077.3299779252296234.18303844692451.191114217
2296260.37713079693420.372531229 2296000.8174884693806.140073136
#Sta/Elev= 30
       0 1964.65    47.4  1959.9   246.4 1954.66   459.2 1954.94   854.8 1951.34
   993.8 1954.99  1045.8 1951.62  1254.1 1950.06  1281.9 1950.48  1317.9 1954.72
  1359.3  1955.3    1410 1949.53    1430 1946.07    1462 1949.51    1490 1949.35
    1534 1951.99  1662.1 1952.42  1690.5 1964.72  1723.9 1968.79  1762.5 1985.21
  1791.4 2000.68    1801 2003.61  1912.9 2007.49  1960.1  2006.4  1967.6 2008.21
  1984.2 2017.09  2032.4 2037.46  2064.7 2046.82  2104.8 2050.45  2178.2 2053.18
#Mann= 13 ,-1,0
       0      .1       0     550     .08       0     710      .1       0
  923.74     .08       0 1123.74      .1       0 1223.74     .07       0
    1410    .045       0    1462     .08       0 1523.74     .07       0
 1813.28     .08       0 1833.28     .03       0 1953.28     .06       0
 2073.28     .03       0
#XS Ineff= 2 , 0
         1357.82 1962.82
Permanent Ineff=
       F       F
Bank Sta=1410,1462
XS Rating Curve= 0 ,0
Exp/Cntr(USF)=0,0
Exp/Cntr=0.3,0.1

Type RM Length L Ch R = 1 ,251     ,,,
XS GIS Cut Line= 3
2296851.16257264692021.8224899352295875.79077818 692483.06758551
2295526.18462293693740.474597649
#Sta/Elev= 30
       0 1961.59    29.9 1961.32    47.6 1958.64   220.1 1954.36   440.4 1955.04
   640.5 1952.19   706.8 1952.39     729 1955.32   770.8 1955.78   998.9 1954.15
  1367.6 1955.65    1405 1954.09  1424.7 1948.18  1446.5 1950.41  1509.1 1950.91
  1570.9 1949.87  1600.1 1944.41  1724.6 1945.33  1753.7 1943.52  1774.5 1945.62
  1911.5 1948.01  1986.2 1950.76  2023.6 1953.95  2065.1 1974.72  2094.1 1994.68
  2107.8 1999.89  2220.6 2017.78  2243.3 2019.37  2339.1 2020.14    2384 2025.21
#Mann= 14 ,-1,0
       0     .08       0      50      .1       0     510     .08       0
     710      .1       0    1040     .07       0 1138.93     .08       0
 1338.93     .07       0 1538.93     .06       0 1678.93     .07       0
  1724.6    .045       0  1774.5     .05       0 1848.93     .08       0
 1948.93     .06       0 2058.93      .1       0
Bank Sta=1724.6,1774.5
XS Rating Curve= 0 ,0
Exp/Cntr(USF)=0,0
Exp/Cntr=0.3,0.1
LCMann Table=0

Chan Stop Cuts=-1
Use User Specified Reach Order=0
Composite Channel Slope=5